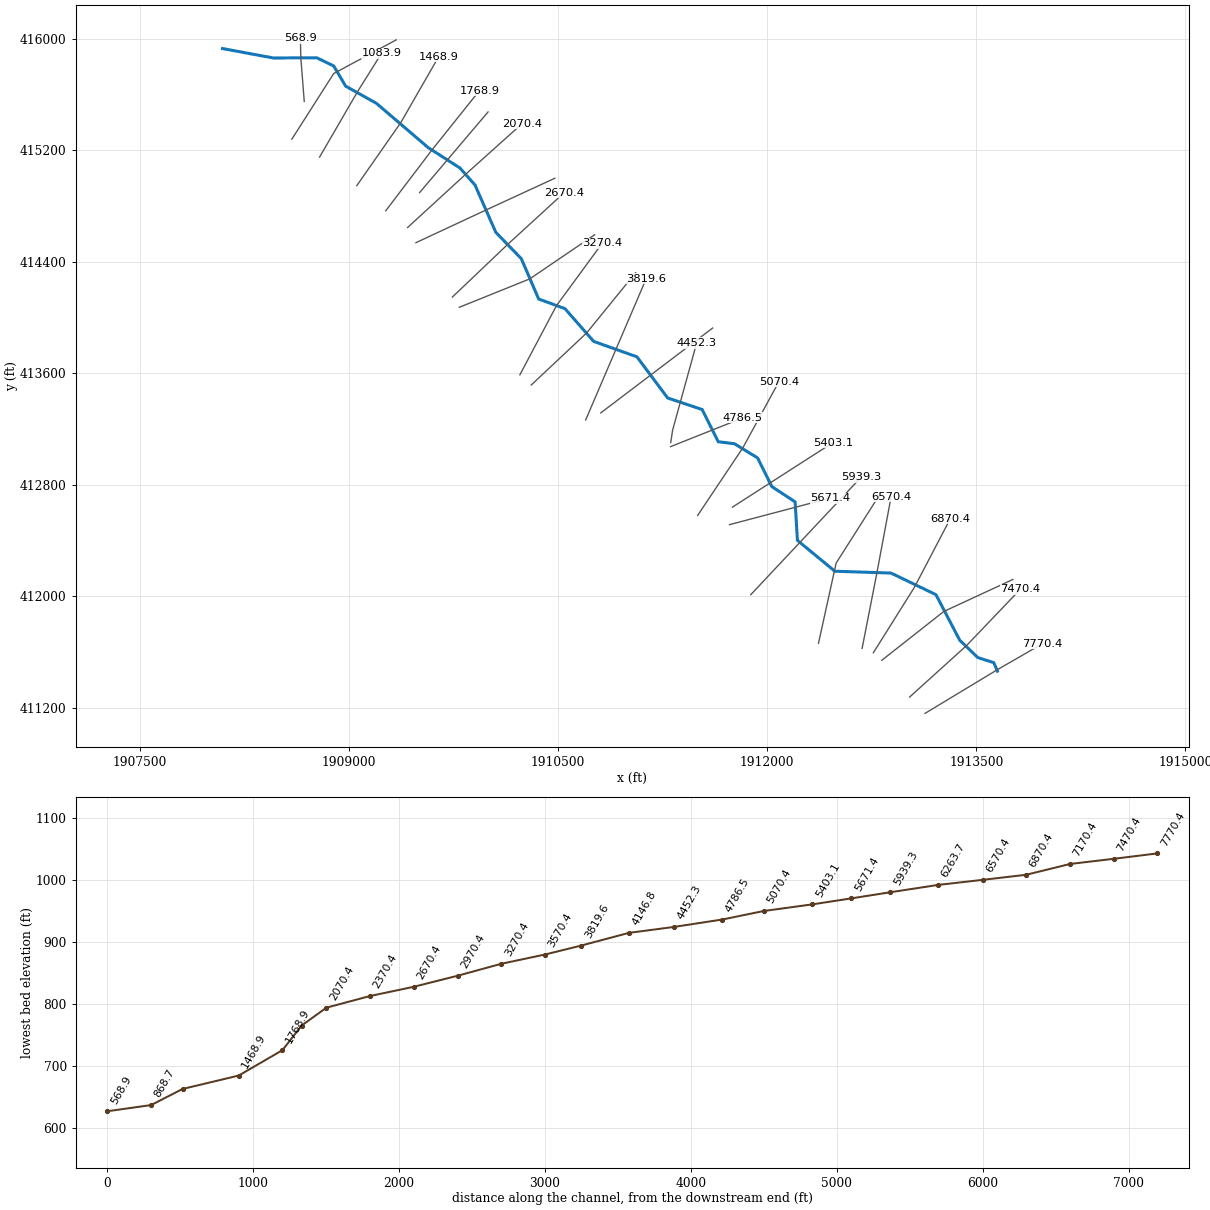
--- FallsCrk.prj (project) ---

Proj Title=FallsCrk
Current Plan=p01
Default Exp/Contr=0,0
English Units
Geom File=g01
Flow File=f01
Plan File=p01
BEGIN DESCRIPTION:
END DESCRIPTION:
DSS Export Rating Curves= 0
DSS Export Rating Curve Sorted= 0
DSS Export Volume Flow Curves= 0
DXF OffsetX= 0
DXF OffsetY= 0
DXF ScaleX= 0
DXF ScaleY= 0

--- FallsCrk.p01 (plan) ---

Plan Title=Floodplain
Program Version=4.00
Geom File=g01
Flow File=f01
K Sum by GR=0
Std Step Tol=0.01
Critical Tol=0.01
Num of Std Step Trials=20
Max Error Tol=0.3
Flow Tol Ratio=0.001
Split Flow NTrial=30
Split Flow Tol=0.02
Split Flow Ratio=0.02
Log Output Level=0
Friction Slope Method=1
Unsteady Friction Slope Method=2
Unsteady Bridges Friction Slope Method=1
Global Log Level=0
CheckData=False
Run HTab=0
Run UNet=0
Run PostProcess=0
UNET Theta=0
UNET Theta Warmup=0
UNET ZTol=0
UNET ZSATol=0
UNET MxIter=0
UNET MaxInSteps=0
UNET DtIC=0
UNET DtMin=0
UNET MaxCRTS=0
UNET WFStab=0
UNET SFStab=0
UNET WFX=0
UNET SFX=0
UNET DSS MLevel=0
UNET DZMax Abort=0
UNET Convert EG Bridges=0
UNET Use Existing IB Tables=0
UNET Froude Limit=0
UNET Froude Power=0
Write IC File=0
Echo Input=False
Echo Output=False
Write Detailed=0

--- FallsCrk.f01 (steady flow) ---

Flow Title=NFF Regression Equation
Program Version=4.00
Number of Profiles=1
Profile Names=P100yr
River Rch & RM=FallsCrk,Main      ,7770.4
882.6886
River Rch & RM=FallsCrk,Main      ,6870.4
950.5514
River Rch & RM=FallsCrk,Main      ,4452.3
1055.084
Boundary for River Rch & Prof#=FallsCrk,Main      ,1
Up Type=0
Dn Type=3
Dn Slope=0.068927

--- FallsCrk.g01 (geometry) ---

Geom Title=USGS 3m DEM
Program Version=4.10

River Reach=FallsCrk        ,Main
Reach XY= 30
     1913651.971      411464.136     1913625.929        411524.9
     1913511.346      411561.358     1913381.138      411686.358
     1913210.999      412012.747     1912888.061      412167.904
     1912485.304       412181.15      1912216.93      412402.172
     1912200.181       412678.49     1912032.857      412788.781
     1911931.485       412993.65     1911765.182      413095.758
     1911648.489      413110.453     1911533.915      413340.872
     1911285.652      413424.205     1911065.165      413719.345
     1910754.402      413830.456     1910548.831       414065.16
     1910360.305      414134.275     1910235.304      414424.206
     1910052.324       414612.98     1909903.707      414951.983
     1909794.841       415074.69     1909566.902       415221.08
     1909195.374      415538.789     1908974.888      415662.053
     1908889.818       415806.15      1908768.29      415865.178
     1908456.344       415863.79     1908091.761      415931.499

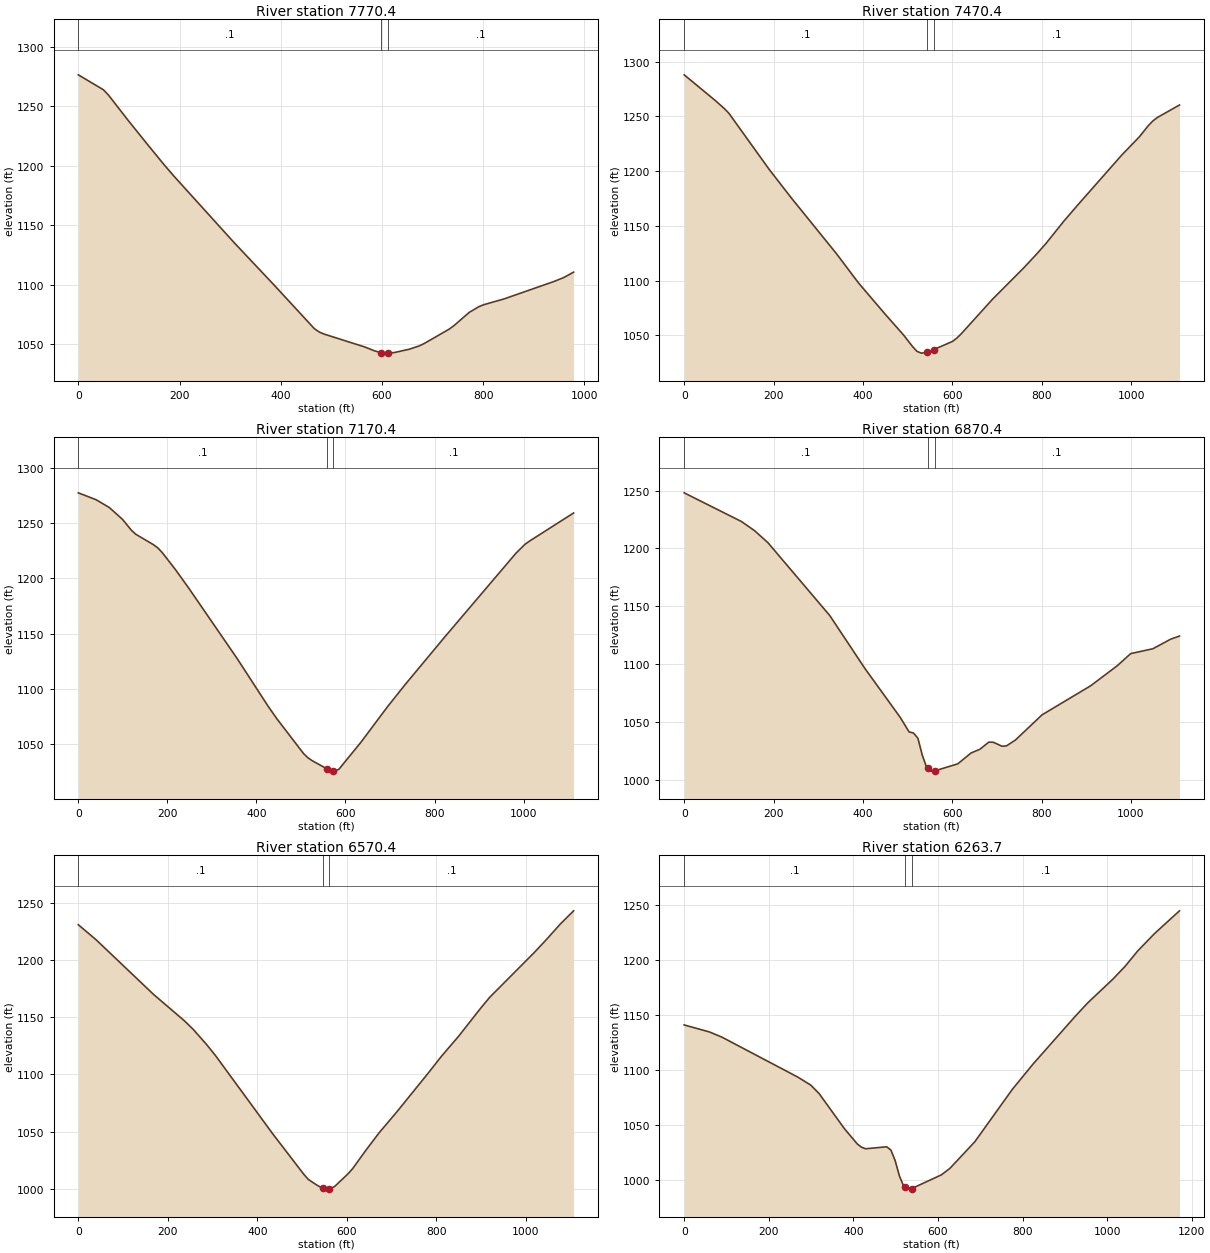
Type RM Length L Ch R = 1 ,7770.4  ,296.3,300,305.9
XS GIS Cut Line= 3
     1913132.554      411161.082      1913650.62      411474.044
     1913974.039      411660.548
#Sta/Elev= 30
       0 1276.34    49.6 1263.79    59.5 1259.39    99.2 1237.67   138.9  1216.7
   168.7 1201.21   188.5  1191.4   307.6 1135.45     387  1099.6   466.4 1063.02
   476.3 1060.11   486.2 1058.38   565.6 1047.68   585.4 1044.35   597.8 1042.89
   605.3 1042.45   612.8 1042.47   624.9 1042.97   654.4 1045.79     674 1048.58
   683.9 1050.64     733 1062.66   742.8 1065.76   772.3 1076.66   791.9  1081.6
   801.8 1083.24     841 1087.97   939.3 1102.58     959 1105.93   978.6 1110.51
#Mann= 3 , 0 , 0
       0      .1       0   597.8    .045       0   612.8      .1       0
Bank Sta=597.8,612.8
XS Rating Curve= 0 ,0
Exp/Cntr=0.3,0.1

Type RM Length L Ch R = 1 ,7470.4  ,300.9,299.8,291.3
XS GIS Cut Line= 3
     1913021.969      411278.263     1913430.215      411647.439
     1913815.364       412050.65
#Sta/Elev= 30
       0 1288.08      70 1264.44    90.1 1257.13   100.1 1252.89   190.1 1201.68
   240.2  1175.3   340.3 1124.82   390.3 1097.72   450.3 1069.01   490.4 1050.49
   510.4    1040   520.4 1035.44   530.4 1033.75   542.9 1034.36   557.9 1036.96
   600.2 1044.44   610.2  1047.6   620.1 1051.56   689.8 1083.03   759.5 1111.61
   789.4 1124.71   809.3 1133.94   849.1 1154.24     879 1168.45   978.6 1214.64
  1018.4  1231.5  1038.3 1241.63  1048.3 1245.88  1058.2 1249.01    1108 1260.52
#Mann= 3 , 0 , 0
       0      .1       0   542.9    .045       0   557.9      .1       0
Bank Sta=542.9,557.9
XS Rating Curve= 0 ,0
Exp/Cntr=0.3,0.1

Type RM Length L Ch R = 1 ,7170.4  ,292.2,299.7,314.8
XS GIS Cut Line= 3
     1912822.665      411542.312     1913266.727      411892.003
      1913763.11      412122.097
#Sta/Elev= 30
       0 1277.56    39.7 1271.36    69.4 1264.31    99.2 1253.54     119 1243.76
   128.9 1240.08   168.6  1230.6   178.5 1227.69   188.4 1223.46   218.2 1207.99
   247.9 1191.28     357 1127.21   426.4 1084.09   446.2 1072.69   505.7 1041.36
   515.6 1037.48   525.6 1034.74   557.7  1027.6   565.2 1025.93   572.7  1025.5
   575.2 1025.36   585.1 1027.01   634.8 1051.58   694.5 1083.79   734.3 1103.94
   823.9 1147.39     983  1222.9  1002.9 1230.84  1012.9 1233.72  1112.3  1259.3
#Mann= 3 , 0 , 0
       0      .1       0   557.7    .045       0   572.7      .1       0
Bank Sta=557.7,572.7
XS Rating Curve= 0 ,0
Exp/Cntr=0.3,0.1

Type RM Length L Ch R = 1 ,6870.4  ,291.4,299.7,306.4
XS GIS Cut Line= 3
     1912761.674      411596.105     1913055.502      412064.425
     1913313.262      412556.959
#Sta/Elev= 30
       0 1248.02   128.3 1223.24     158 1215.25   187.6 1204.96   325.8 1142.23
   404.8 1096.39   483.8 1054.25   503.5 1041.78   513.4 1040.83   523.2 1036.35
   533.1 1021.59     543    1011   545.4 1010.26   552.9 1007.96   560.4 1008.12
   612.4 1014.22   642.2  1023.6   662.1 1026.85   681.9 1032.98   691.8 1032.89
   711.7 1029.43   721.6 1029.76   741.5 1034.77     801 1056.48   910.2 1081.64
   969.8 1098.97   999.6 1109.34  1049.2 1113.51  1088.9 1121.75  1108.8 1124.48
#Mann= 3 , 0 , 0
       0      .1       0   545.4    .045       0   560.4      .1       0
Bank Sta=545.4,560.4
XS Rating Curve= 0 ,0
Exp/Cntr=0.3,0.1

Type RM Length L Ch R = 1 ,6570.4  ,307.3,306.8,306.1
XS GIS Cut Line= 3
      1912680.97      411627.518     1912787.338      412170.621
     1912888.872      412714.239
#Sta/Elev= 30
       0 1230.86    39.5 1217.79     168 1169.96   237.2 1146.82     257 1139.26
   286.6 1126.13   306.4 1116.51   434.8 1047.84     504 1012.58   513.9  1008.2
   533.7 1003.06   545.9 1000.56   553.4  999.74   560.9  999.97   563.3 1000.04
   573.2 1002.26   602.8 1013.22   612.7 1017.61   642.3 1033.66   671.9 1048.93
   711.4  1067.2   780.6 1100.64   810.2 1115.38   849.7 1133.44   899.1 1158.01
   918.8 1167.32  1017.6 1206.17  1047.2 1218.53  1076.8 1231.49  1106.4 1242.99
#Mann= 3 , 0 , 0
       0      .1       0   545.9    .045       0   560.9      .1       0
Bank Sta=545.9,560.9
XS Rating Curve= 0 ,0
Exp/Cntr=0.3,0.1

Type RM Length L Ch R = 1 ,6263.7  ,336.5,324.3,312
XS GIS Cut Line= 3
     1912368.072      411664.553     1912494.595      412239.333
     1912807.191       412731.08
#Sta/Elev= 30
       0 1140.69    59.8 1134.33    89.8  1129.5   269.3 1093.17   299.3 1086.03
   319.2 1078.25   379.1 1046.36     409 1032.71     419 1029.67   428.9 1028.18
   478.8 1029.98   488.8 1027.04   498.8 1017.53   508.7 1003.78   518.7   994.5
     523  993.21   528.7  991.51     538  992.03   608.3  1004.5     628 1010.25
   687.3 1034.59   776.2  1082.3   825.6 1105.45   924.3 1148.38     954 1160.66
  1013.2 1182.11  1042.8 1194.04  1072.5 1207.95    1112 1223.64  1171.2 1244.38
#Mann= 3 , 0 , 0
       0      .1       0     523    .045       0     538      .1       0
Bank Sta=523,538
XS Rating Curve= 0 ,0
Exp/Cntr=0.3,0.1

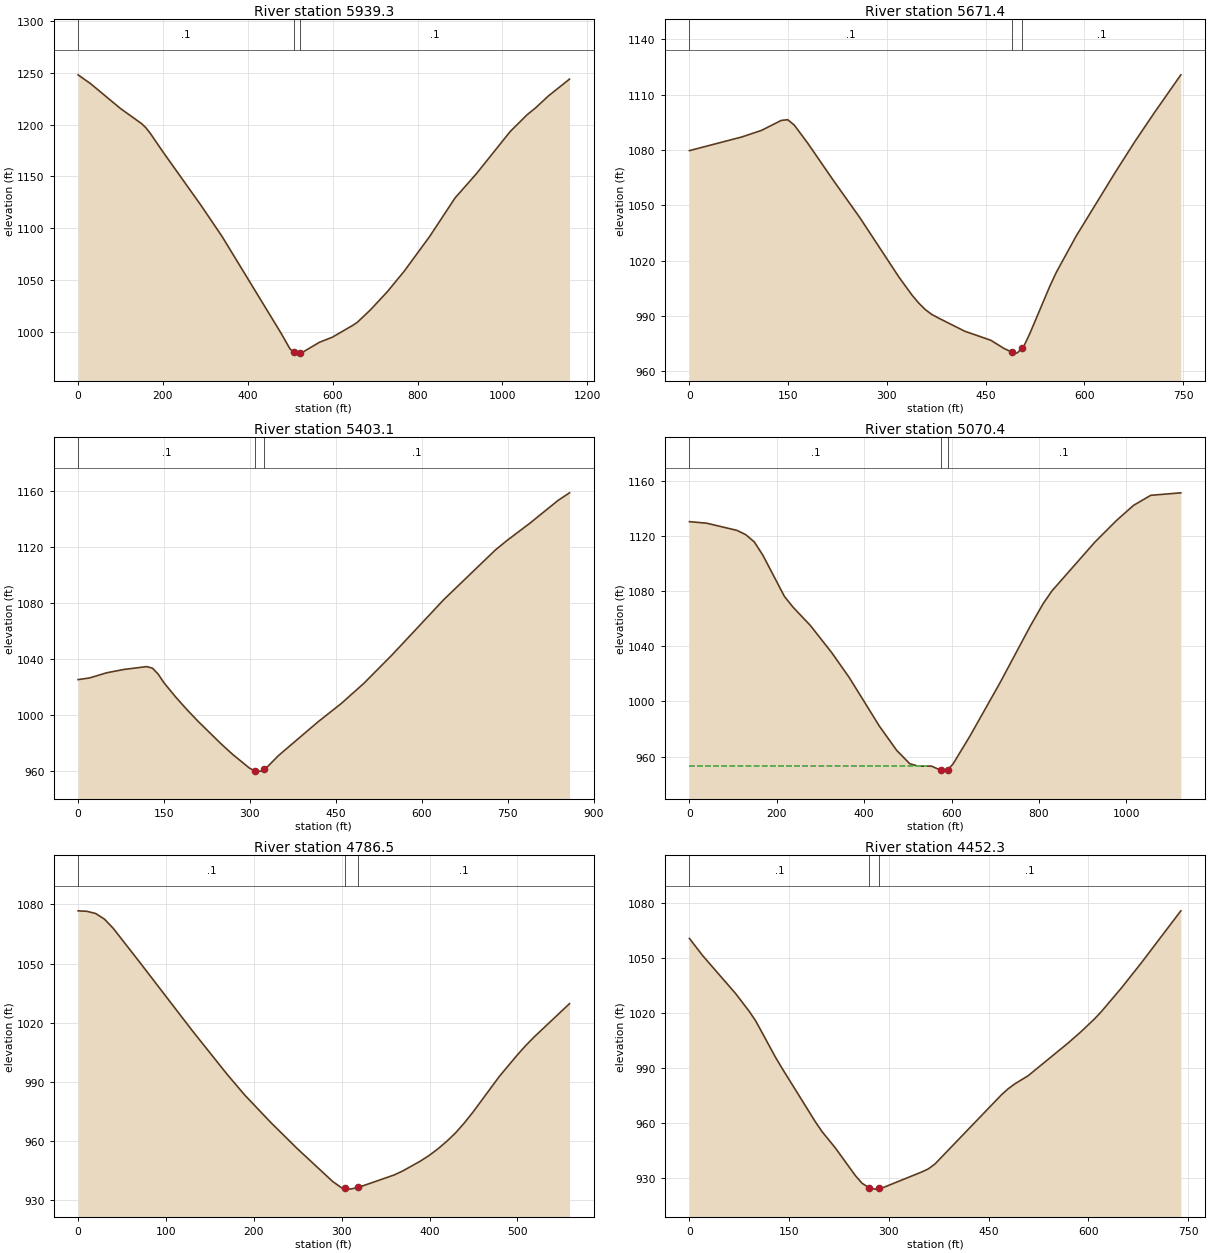
Type RM Length L Ch R = 1 ,5939.3  ,280.6,267.7,254.7
XS GIS Cut Line= 2
     1911882.062      412012.596     1912674.871      412856.864
#Sta/Elev= 30
       0 1247.84      30 1239.13    99.8 1215.42   149.8 1200.79   159.8 1196.87
   169.7 1191.72   199.7  1173.8   289.5 1122.22   339.5 1092.05   479.2  998.44
   499.2     984   508.6   980.5   519.2  979.81   523.6   980.2   529.2  980.69
   569.1  990.32     599   995.1     649 1006.96     659 1009.83   688.9 1021.44
   728.8 1038.96   768.8 1058.82   828.7 1092.25   888.6 1129.34   938.5 1152.47
  1018.4 1193.23  1058.3 1209.42  1078.3 1216.02  1108.2 1227.42  1158.2 1243.71
#Mann= 3 , 0 , 0
       0      .1       0   508.6    .045       0   523.6      .1       0
Bank Sta=508.6,523.6
XS Rating Curve= 0 ,0
Exp/Cntr=0.3,0.1

Type RM Length L Ch R = 1 ,5671.4  ,261.2,268.2,275.3
XS GIS Cut Line= 2
     1911729.773      412515.436     1912451.777      412705.904
#Sta/Elev= 30
       0 1079.61    79.6 1087.01   109.5 1090.58   139.4 1095.96   149.3 1096.37
   159.3 1093.46   179.2 1083.93     219 1063.33   258.9 1043.31   318.6 1010.94
   338.5 1001.19   348.5  996.98   358.4  993.46   368.4  990.81   378.3  988.92
   418.2  981.77     458  976.84   477.9  972.43   490.7  970.31   497.8  969.88
   505.7  972.61   507.8  973.34   517.7  980.87   547.6 1006.13   557.5  1013.7
   587.4 1033.16   647.1 1067.88     677  1084.6   706.9 1100.39   746.7 1120.68
#Mann= 3 , 0 , 0
       0      .1       0   490.7    .045       0   505.7      .1       0
Bank Sta=490.7,505.7
XS Rating Curve= 0 ,0
Exp/Cntr=0.3,0.1

Type RM Length L Ch R = 1 ,5403.1  ,323.2,332.6,343.9
XS GIS Cut Line= 2
     1911750.444      412640.938     1912472.448      413104.556
#Sta/Elev= 30
       0 1025.35      20 1026.55    49.9 1030.22    79.8 1032.58   119.7 1034.62
   129.7 1033.55   139.7 1029.32   149.7 1023.23   169.6 1013.32   189.6 1004.16
   209.5  995.66   249.4   979.7   269.4  972.24   299.3  962.27   309.3  960.16
   319.3  960.16   324.3  961.44   329.2  962.69   349.2  970.99   359.2  974.51
     419   995.3     459 1008.17   498.9 1022.68   548.8 1043.24   638.5 1082.36
   728.3  1117.6   748.3  1124.3   788.2 1136.57   838.1 1153.04     858 1158.42
#Mann= 3 , 0 , 0
       0      .1       0   309.3    .045       0   324.3      .1       0
Bank Sta=309.3,324.3
XS Rating Curve= 0 ,0
Exp/Cntr=0.3,0.1

Type RM Length L Ch R = 1 ,5070.4  ,297.3,283.5,267.8
XS GIS Cut Line= 3
     1911500.879      412581.557     1911825.288      413066.636
     1912084.439       413542.04
#Sta/Elev= 30
       0  1130.2    39.6 1129.08   108.8 1123.88   128.6 1120.84   148.4 1115.56
   168.1  1105.9   217.6 1075.97   237.4 1068.18   276.9 1054.98   326.4 1035.04
     366 1017.23   435.2  981.91   474.8  964.41   504.4  954.86   524.2  953.07
   553.9  953.14   576.1  950.04   583.6  949.49   591.1  950.47   603.2  954.55
   642.6  975.12   711.5 1013.76   780.4 1054.62     810 1070.91   829.7 1079.96
   928.1 1115.36   977.3 1130.94  1016.7    1142  1056.1 1149.28    1125 1151.08
#Mann= 3 , 0 , 0
       0      .1       0   576.1    .045       0   591.1      .1       0
#XS Ineff= 2 , 0
          543.33  953.41
Permanent Ineff=
       F       F
Bank Sta=576.1,591.1
XS Rating Curve= 0 ,0
Exp/Cntr=0.3,0.1

Type RM Length L Ch R = 1 ,4786.5  ,312.6,333.9,355.2
XS GIS Cut Line= 2
     1911306.389      413075.026     1911826.114      413281.735
#Sta/Elev= 30
       0 1076.79      10 1076.55      20 1075.42      30 1072.58      40 1067.91
    69.9 1050.87   129.8 1016.16   169.8  993.84   189.8  983.37   219.7  969.36
   249.7  956.18   289.6  939.69   299.6  936.51   303.8   936.2   309.6  935.76
   318.8  936.61   359.6  942.91   369.6     945   389.5  949.94   399.5   952.8
   409.5  956.16   419.5  959.95   429.5  964.21   439.5  969.25   449.5  974.82
   479.4  992.86   499.4  1003.5   509.4 1008.48   519.4 1013.02   559.3 1029.75
#Mann= 3 , 0 , 0
       0      .1       0   303.8    .045       0   318.8      .1       0
Bank Sta=303.8,318.8
XS Rating Curve= 0 ,0
Exp/Cntr=0.3,0.1

Type RM Length L Ch R = 1 ,4452.3  ,320.3,305.6,290.8
XS GIS Cut Line= 3
     1911307.865      413104.556     1911321.154      413193.146
     1911493.903      413819.178
#Sta/Elev= 30
       0 1060.86    19.9 1051.46    69.7 1030.59    89.6 1021.12    99.6 1015.77
   129.6  995.73   139.5  989.71   189.5  960.45   199.5  955.15   219.5  946.19
   249.4  931.17   259.4  926.98   270.5  924.35   279.4   923.7   285.5  924.05
   289.4  924.27   349.4  933.09   359.3  934.77   369.3  937.48   469.2  975.29
   479.2  978.57   489.2  981.26   509.2   985.7   569.2 1003.56   589.1  1009.9
   609.1 1016.81   619.1 1020.67   649.1 1033.52   679.1 1047.27     739 1075.96
#Mann= 3 , 0 , 0
       0      .1       0   270.5    .045       0   285.5      .1       0
Bank Sta=270.5,285.5
XS Rating Curve= 0 ,0
Exp/Cntr=0.3,0.1

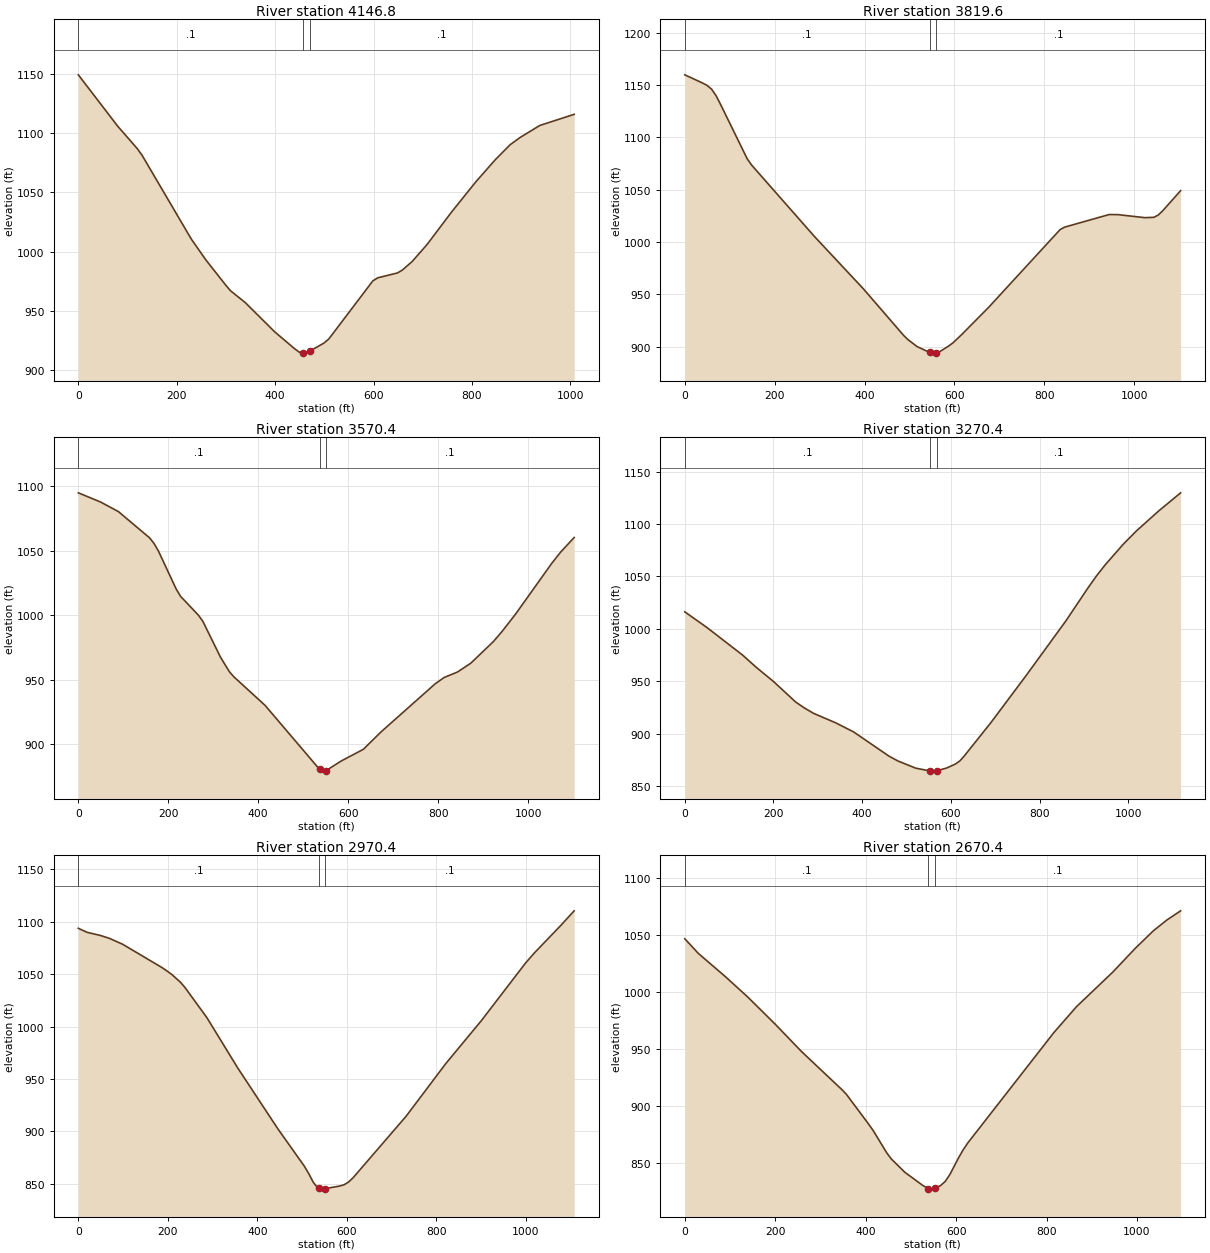
Type RM Length L Ch R = 1 ,4146.8  ,315.5,327.1,338.8
XS GIS Cut Line= 2
     1910805.859      413317.171     1911608.532      413926.116
#Sta/Elev= 30
       0 1149.32    79.8 1106.04   119.7 1087.02   129.7 1081.26   229.4 1010.68
   259.4  992.84   299.3   971.8   309.2  966.94   339.2  956.94     399  932.23
   438.9  918.16   448.9  915.04   455.7   914.5   458.9  914.24   470.7  916.01
   498.8  922.67   508.8  926.11   598.5   975.3   608.5  977.86   648.4  981.95
   658.4   984.4   678.3  991.62   708.3 1005.83   758.1 1033.25     808  1059.1
   847.9 1077.91   877.8 1090.41   897.8 1096.42   937.7 1106.55  1007.5 1115.96
#Mann= 3 , 0 , 0
       0      .1       0   455.7    .045       0   470.7      .1       0
Bank Sta=455.7,470.7
XS Rating Curve= 0 ,0
Exp/Cntr=0.3,0.1

Type RM Length L Ch R = 1 ,3819.6  ,258.4,249.1,242.6
XS GIS Cut Line= 2
     1910697.312      413266.328     1911131.894      414280.374
#Sta/Elev= 30
       0 1159.89    39.8 1152.01    49.7 1149.71    59.6 1146.19    69.6 1139.96
    79.5 1131.69   139.2 1079.31   149.1  1073.4   288.2 1005.44   397.6  955.14
     487  910.68     497  906.53   516.8  900.06   544.5  894.46   556.6  893.78
   559.5  894.13   566.5  894.99   586.4  900.39   596.4  903.52   616.2  911.57
   675.9   937.5   834.9 1011.83   844.8 1014.21   944.2 1026.31   964.1 1026.19
  1023.7 1023.31  1043.6 1023.64  1053.6 1025.87  1063.5 1029.97  1103.2 1049.11
#Mann= 3 , 0 , 0
       0      .1       0   544.5    .045       0   559.5      .1       0
Bank Sta=544.5,559.5
XS Rating Curve= 0 ,0
Exp/Cntr=0.3,0.1

Type RM Length L Ch R = 1 ,3570.4  ,292.4,299.7,300.5
XS GIS Cut Line= 3
     1910306.984       413517.26       1910703.3      413889.558
     1911055.862      414322.978
#Sta/Elev= 30
       0 1094.81    49.4  1087.7      89 1080.31   158.2 1060.02   168.1 1055.72
     178 1049.84   217.5 1020.35   227.4 1014.62   266.9  1000.1   276.8  995.34
   316.4  967.32   336.1  956.15     346  952.25   415.2  930.22   536.3  880.67
   543.8  879.27   551.3  879.73   583.7  886.96   633.6  896.13   673.5  909.78
   793.2   946.8   813.1  951.74   843.1  956.03     873  962.96   922.9  979.62
   942.8  987.71   972.8 1001.16  1052.6 1040.16  1072.5 1048.94  1102.5  1060.2
#Mann= 3 , 0 , 0
       0      .1       0   536.3    .045       0   551.3      .1       0
Bank Sta=536.3,551.3
XS Rating Curve= 0 ,0
Exp/Cntr=0.3,0.1

Type RM Length L Ch R = 1 ,3270.4  ,315.8,300.4,293.5
XS GIS Cut Line= 3
      1910225.29      413590.269     1910487.686      414086.076
     1910816.905       414535.62
#Sta/Elev= 30
       0 1016.28    50.1 1001.27   130.2  975.09   160.3  963.65   200.3  949.71
   250.4  930.11   270.5  924.36   290.5  919.41   340.6  910.33   380.6  901.73
   460.8  878.54   480.8  873.98   520.9  867.13   553.5  864.45     561  864.31
   568.5  864.66   590.8   867.3   610.7  871.16   620.7  874.17   630.6  878.93
   690.3  910.58   769.9  955.55   859.5 1007.69   909.2 1039.05   929.1 1050.93
     949 1061.58   988.8 1080.77  1018.7 1093.55  1068.4 1112.39  1118.2 1129.82
#Mann= 3 , 0 , 0
       0      .1       0   553.5    .045       0   568.5      .1       0
Bank Sta=553.5,568.5
XS Rating Curve= 0 ,0
Exp/Cntr=0.3,0.1

Type RM Length L Ch R = 1 ,2970.4  ,291.2,299.5,302.6
XS GIS Cut Line= 3
     1909791.021      414075.053     1910296.214      414278.633
     1910762.121      414595.421
#Sta/Elev= 30
       0 1093.67    19.8  1089.8    49.5 1086.82    69.3  1084.1      99 1078.47
   188.2  1055.9     208 1049.96   227.8 1042.42   237.7 1037.58   287.2 1008.55
   356.5  960.33   445.6  902.64   505.1  866.83     515  859.68   524.9   851.6
   534.8  846.18   537.2  845.88   544.7  844.94   552.2  845.44   584.2   847.9
   594.1  849.14     604  851.75   613.9  855.71   732.5  914.42   821.4  964.76
   900.5 1005.48   999.4  1060.5  1019.1 1070.14  1078.4 1096.46  1108.1 1110.33
#Mann= 3 , 0 , 0
       0      .1       0   537.2    .045       0   552.2      .1       0
Bank Sta=537.2,552.2
XS Rating Curve= 0 ,0
Exp/Cntr=0.3,0.1

Type RM Length L Ch R = 1 ,2670.4  ,307.2,299.8,292.8
XS GIS Cut Line= 3
     1909740.957      414148.336     1910136.346      414524.817
     1910542.532      414896.514
#Sta/Elev= 30
       0 1046.44    29.8 1033.66    89.3 1013.41     139  995.49   198.5   972.2
   258.1  947.68   347.4  914.32   357.4   910.2     407  883.88   416.9  878.31
   446.7  858.92   456.6  853.65   486.4  842.02   526.1  830.45   538.5  827.66
     546  827.16   553.5  827.96     566  830.39     576  833.94     586  839.78
     606  854.95     616   861.8     626  867.65   816.2  964.23   866.3  986.95
   946.4 1017.16   996.4 1038.09  1036.5 1053.48  1066.5 1062.93  1096.6 1070.89
#Mann= 3 , 0 , 0
       0      .1       0   538.5    .045       0   553.5      .1       0
Bank Sta=538.5,553.5
XS Rating Curve= 0 ,0
Exp/Cntr=0.3,0.1

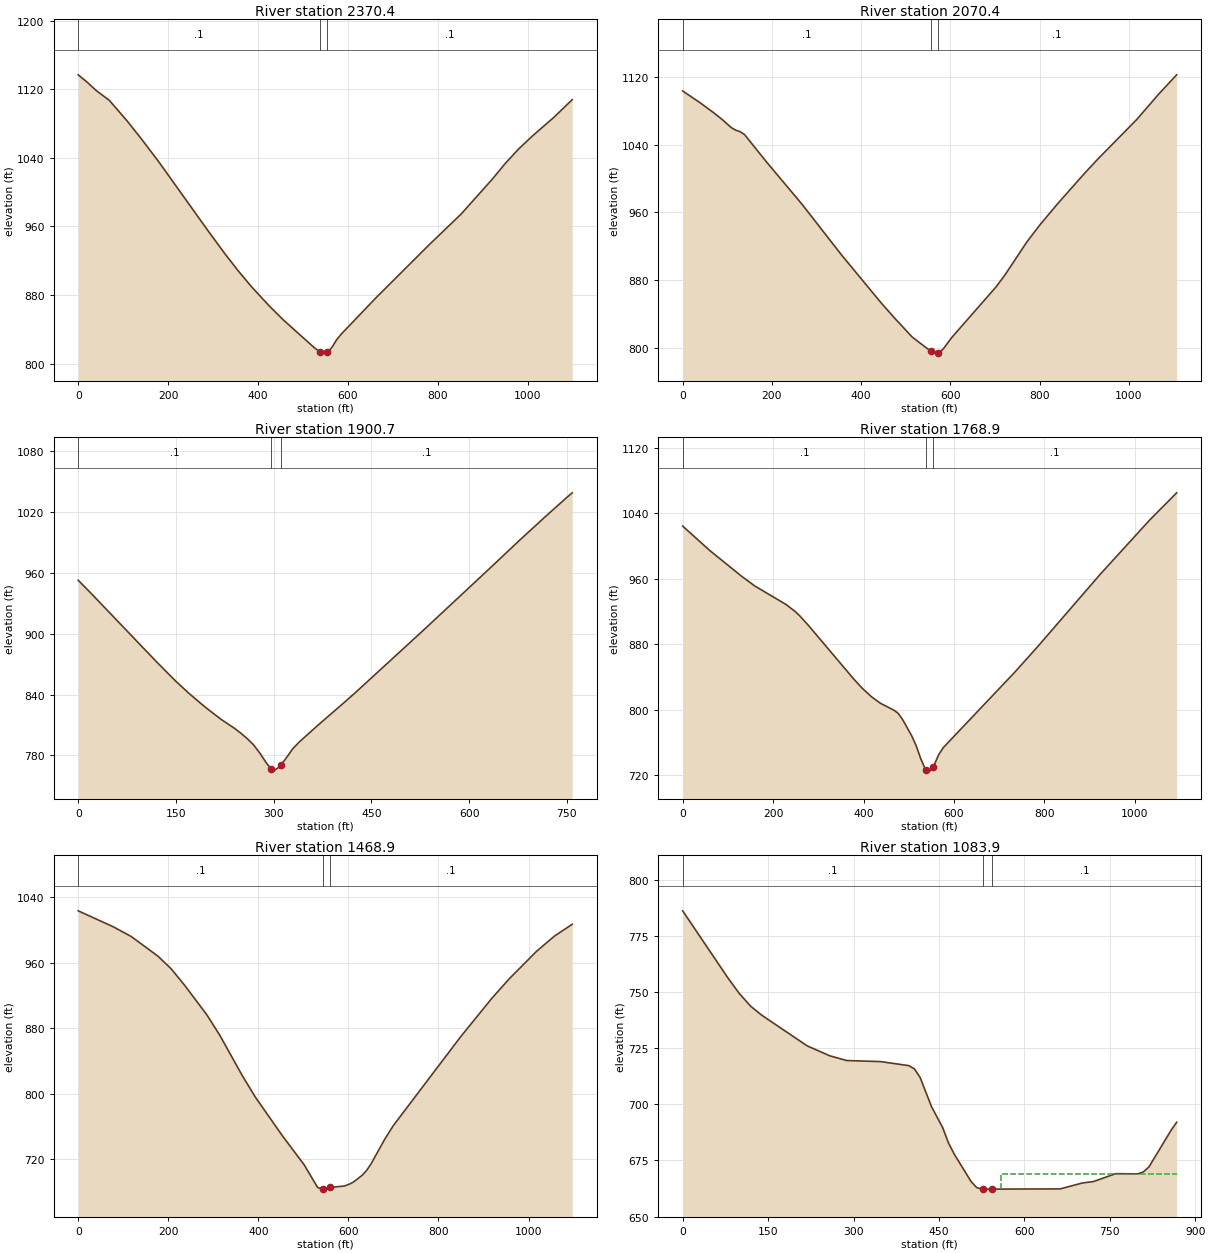
Type RM Length L Ch R = 1 ,2370.4  ,293.1,300,306.8
XS GIS Cut Line= 3
     1909479.638      414538.595     1909973.217      414768.753
     1910476.174      415000.799
#Sta/Elev= 30
       0 1136.69    19.8 1128.14    39.6 1118.57    69.3 1106.87   108.9 1082.83
   138.6 1063.23   178.2 1035.96   287.2  955.97   326.8   927.7   356.5  907.74
   386.2   889.2   425.8  866.73   455.5  851.31   524.8   818.7   537.1  813.92
   544.6   812.3   552.1  813.12   554.5  813.38   564.4  819.16   574.3  827.66
   584.2  834.09   663.3  877.44     782  939.44   851.2  974.26   920.5  1014.9
   950.1 1033.68   979.8  1050.5  1009.5 1065.16  1058.9 1087.71  1098.5  1107.8
#Mann= 3 , 0 , 0
       0      .1       0   537.1    .045       0   552.1      .1       0
Bank Sta=537.1,552.1
XS Rating Curve= 0 ,0
Exp/Cntr=0.3,0.1

Type RM Length L Ch R = 1 ,2070.4  ,166.4,169.1,172.1
XS GIS Cut Line= 3
     1909419.794      414647.334      1909835.39      415028.584
     1910239.562      415390.946
#Sta/Elev= 30
       0 1103.53    39.6 1089.35    69.3 1077.83      89 1069.52   108.8 1060.22
   118.7 1057.16   128.6 1055.32   138.5 1052.02     188 1019.44   267.2  969.62
   356.2  909.37   445.2  852.51   474.9  834.81   514.5   812.3   556.5  795.45
     564  793.37   571.5  793.49   573.8  793.53   583.7  798.25   603.5   812.2
   702.2  871.76   721.9  885.65   771.2  924.92   800.8  945.35   840.3  970.19
   899.5 1005.49   929.2  1022.4    1018  1070.1  1067.3 1100.24  1106.8  1122.6
#Mann= 3 , 0 , 0
       0      .1       0   556.5    .045       0   571.5      .1       0
Bank Sta=556.5,571.5
XS Rating Curve= 0 ,0
Exp/Cntr=0.3,0.1

Type RM Length L Ch R = 1 ,1900.7  ,130.6,131.9,132.7
XS GIS Cut Line= 2
     1909506.362      414898.493     1909996.926      415476.539
#Sta/Elev= 30
       0  952.63      20  939.55   119.7  872.61   149.6  853.26   169.6  841.44
   189.5  830.53   199.5  825.33   219.5  815.51   239.4  806.96   249.4   802.1
   259.4  796.62   269.3  790.36   279.3  781.85   289.3  772.16     296  767.09
   299.3   764.6   309.2  768.98     311  770.52   319.2  777.52   329.2  786.57
   339.2  793.29   369.1  810.48     409  832.65     429  844.06   528.7  902.75
   628.5  962.45   678.3  992.55   718.2 1016.01   748.2 1033.24   758.2 1038.74
#Mann= 3 , 0 , 0
       0      .1       0     296    .045       0     311      .1       0
Bank Sta=296,311
XS Rating Curve= 0 ,0
Exp/Cntr=0.3,0.1

Type RM Length L Ch R = 1 ,1768.9  ,298.8,299.8,303.2
XS GIS Cut Line= 3
     1909262.822      414767.323     1909593.411      415202.368
     1909934.431      415628.748
#Sta/Elev= 30
       0 1024.54    59.6  994.82   129.2  963.67     159  951.45   228.5  928.67
   248.4  920.23   258.3  915.12   278.2  903.03   377.5  837.98   397.4  826.05
   417.2  815.97   437.1  807.88   466.9  799.47   476.9  795.38   486.8  787.55
   506.7   767.8   516.6  755.61   526.5  740.02   536.5  727.32   538.9  726.72
   546.4  724.84   553.9  730.47   556.3  732.27   566.2  745.01   576.2   753.5
     735  846.19   784.6  876.79   923.6  965.72  1032.8 1031.94  1092.4  1065.2
#Mann= 3 , 0 , 0
       0      .1       0   538.9    .045       0   553.9      .1       0
Bank Sta=538.9,553.9
XS Rating Curve= 0 ,0
Exp/Cntr=0.3,0.1

Type RM Length L Ch R = 1 ,1468.9  ,383,384.9,384.5
XS GIS Cut Line= 3
     1909055.322      414947.948     1909370.545      415399.909
     1909642.741      415873.218
#Sta/Elev= 30
       0 1023.01    78.7 1003.31   118.1  991.56   177.1  967.72   206.6  952.23
   236.2  932.37   285.4   896.5   314.9  870.91   364.1  822.35   393.6  795.77
   452.6  749.47   501.8  713.47   531.4  686.02   541.2  683.86   543.5   684.1
   558.5  685.95   590.7  687.62   600.7  689.63   610.6  692.28   630.4  700.65
   640.4  706.66   650.3  714.65   680.1  744.15   699.9  761.42   848.8  869.26
   918.3  916.28     958  940.69  1017.6  973.57  1057.3  992.12    1097 1006.65
#Mann= 3 , 0 , 0
       0      .1       0   543.5    .045       0   558.5      .1       0
Bank Sta=543.5,558.5
XS Rating Curve= 0 ,0
Exp/Cntr=0.3,0.1

Type RM Length L Ch R = 1 ,1083.9  ,227.8,215.3,203.2
XS GIS Cut Line= 3
     1908788.057      415152.635     1909062.227      415625.073
     1909232.842      415897.339
#Sta/Elev= 30
       0   786.4    79.4  756.49    99.3  749.58   119.2  743.87     139  739.81
   218.5  726.17   258.2  721.72     288   719.6   347.6  719.12   397.3  717.32
   407.2   715.8   417.1     712     437  699.02   456.8  689.57   466.8  682.82
   476.7  677.94   506.5  665.61   516.4  662.89   526.4  662.22   528.1  662.22
   543.1  662.23   663.1  662.32     702  664.97   721.5   665.6   760.4  669.12
   799.4  669.02   809.1  669.93   818.8  672.11   857.8   688.5   867.5  692.03
#Mann= 3 , 0 , 0
       0      .1       0   528.1    .045       0   543.1      .1       0
#XS Ineff= 2 , 0
                          559.85           669.1
Permanent Ineff=
       F       F
Bank Sta=528.1,543.1
XS Rating Curve= 0 ,0
Exp/Cntr=0.3,0.1

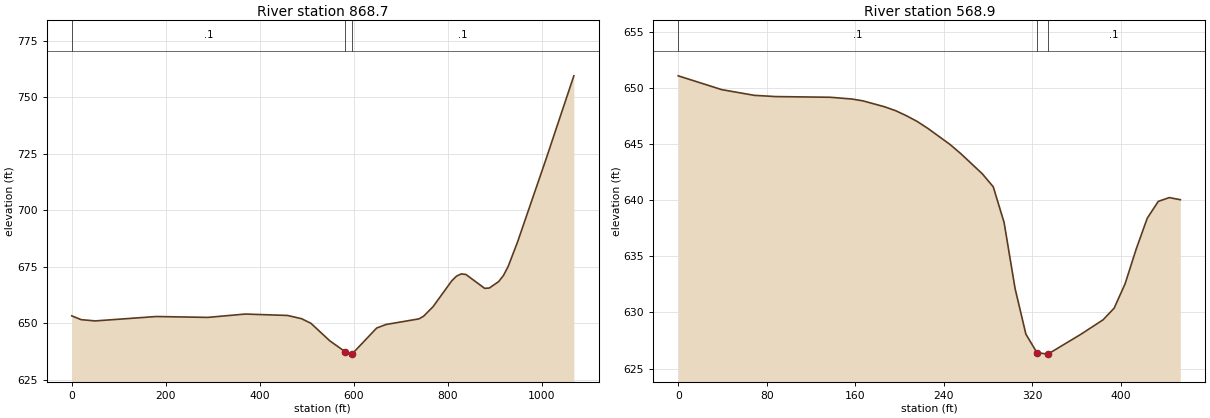
Type RM Length L Ch R = 1 ,868.7   ,273.4,299.6,324.5
XS GIS Cut Line= 3
     1908589.136       415281.23     1908889.558      415752.273
     1909338.042       415993.68
#Sta/Elev= 30
       0  653.19      20  651.51    49.9  650.95   179.6   652.9   289.3  652.51
   369.1  653.99   458.9  653.37   488.8  651.94   508.8  649.89   548.7  642.18
   581.8  637.28   588.6  636.26   596.8  636.44   648.6  647.81   668.6  649.38
   738.4  651.85   748.4  653.03   768.4  657.22   808.4  668.71   818.4  670.77
   828.3  671.74   838.3  671.52   878.3  665.36   888.3  665.51   908.2  668.38
   918.2  671.04   928.2  675.01   948.2  685.84  1008.1  722.09    1068  759.38
#Mann= 3 , 0 , 0
       0      .1       0   581.8    .045       0   596.8      .1       0
Bank Sta=581.8,596.8
XS Rating Curve= 0 ,0
Exp/Cntr=0.3,0.1

Type RM Length L Ch R = 1 ,568.9   ,574.2,568.8,564.5
XS GIS Cut Line= 3
     1908678.051       415551.84      1908653.58      415865.178
     1908650.367      416004.753
#Sta/Elev= 30
       0  651.09    39.3  649.86    68.8  649.35    88.4  649.24   137.5  649.18
   157.2  649.02     167  648.86   186.6  648.33   196.4  647.99   206.2  647.54
   216.1  647.02   225.9  646.39   245.5  644.99   255.4  644.16     275  642.35
   284.8   641.2   294.6  638.02   304.5  632.15   314.3  628.07   324.3  626.42
   334.2  626.29   364.2  628.07   384.1  629.35   394.1  630.39     404  632.56
     414  635.65     424   638.4     434   639.9   443.9  640.24   453.9  640.05
#Mann= 3 , 0 , 0
       0      .1       0   324.3    .045       0   334.2      .1       0
Bank Sta=324.3,334.2
XS Rating Curve= 0 ,0
Exp/Cntr=0.3,0.1

Chan Stop Cuts=-1
Use User Specified Reach Order=0
Composite Channel Slope=5